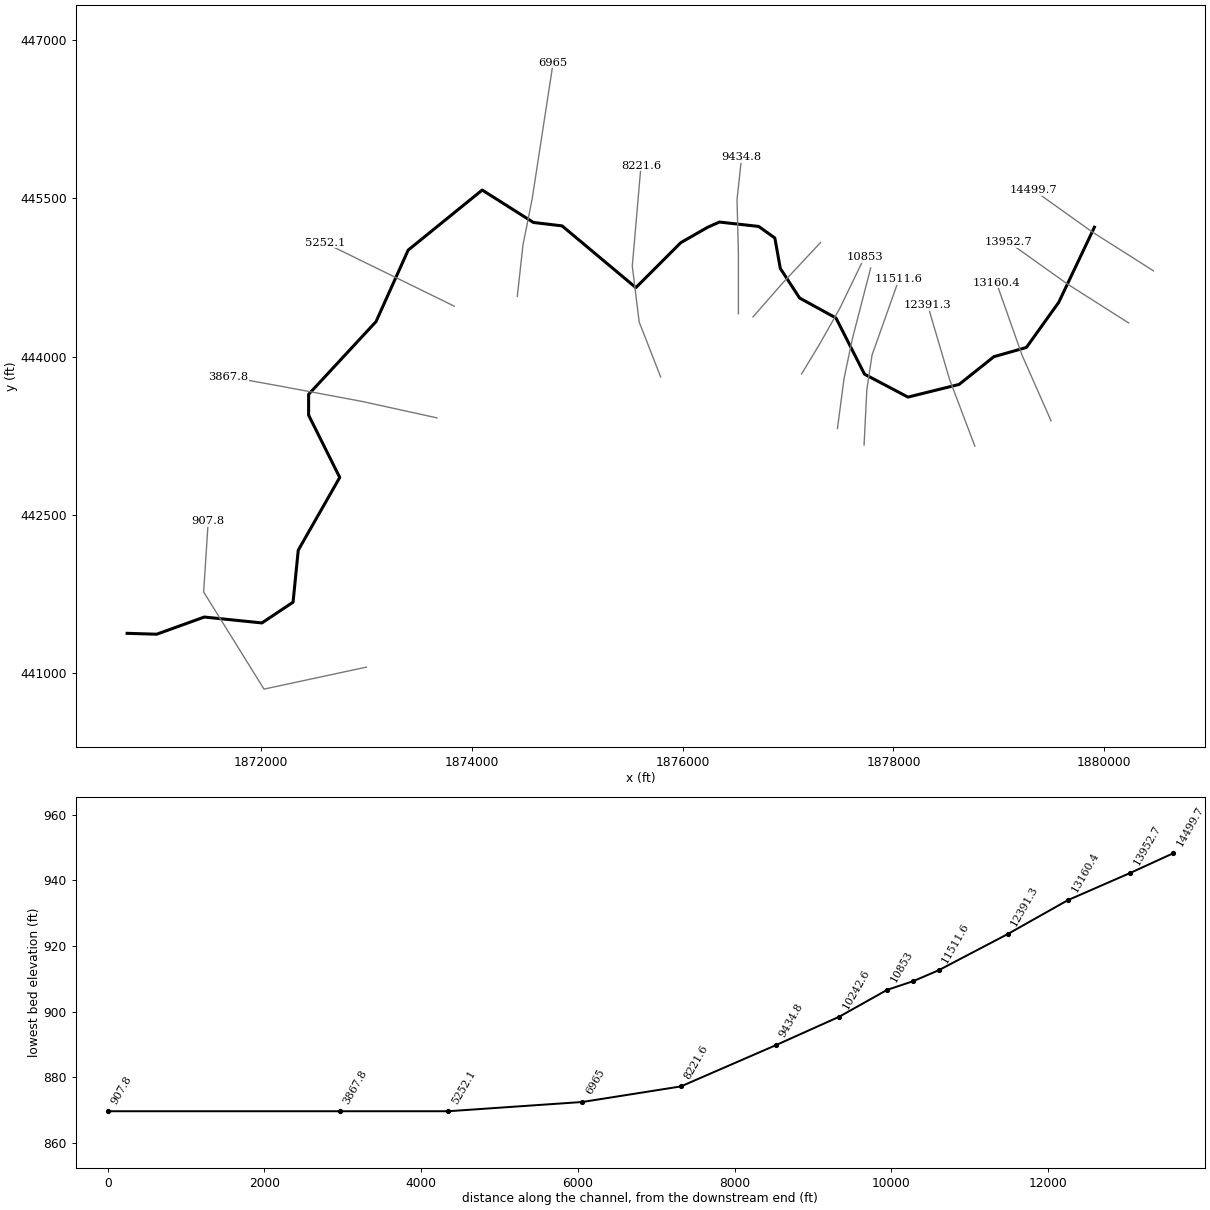
--- RublesRun.prj (project) ---

Proj Title=RublesRun
Current Plan=p01
Default Exp/Contr=0,0
English Units
Geom File=g01
Flow File=f01
Plan File=p01
BEGIN DESCRIPTION:
Used Known WSEL from Cheat River (Average of U/S & D/S Cheat River XS)
END DESCRIPTION:
DSS Export Rating Curves= 0
DSS Export Rating Curve Sorted= 0
DSS Export Volume Flow Curves= 0
DXF OffsetX= 0
DXF OffsetY= 0
DXF ScaleX= 0
DXF ScaleY= 0

--- RublesRun.p01 (plan) ---

Plan Title=Floodplain
Program Version=4.00
Geom File=g01
Flow File=f01
K Sum by GR=0
Std Step Tol=0.01
Critical Tol=0.01
Num of Std Step Trials=20
Max Error Tol=0.3
Flow Tol Ratio=0.001
Split Flow NTrial=30
Split Flow Tol=0.02
Split Flow Ratio=0.02
Log Output Level=0
Friction Slope Method=1
Unsteady Friction Slope Method=2
Unsteady Bridges Friction Slope Method=1
Global Log Level=0
CheckData=False
Run HTab=0
Run UNet=0
Run PostProcess=0
UNET Theta=0
UNET Theta Warmup=0
UNET ZTol=0
UNET ZSATol=0
UNET MxIter=0
UNET MaxInSteps=0
UNET DtIC=0
UNET DtMin=0
UNET MaxCRTS=0
UNET WFStab=0
UNET SFStab=0
UNET WFX=0
UNET SFX=0
UNET DSS MLevel=0
UNET DZMax Abort=0
UNET Convert EG Bridges=0
UNET Use Existing IB Tables=0
UNET Froude Limit=0
UNET Froude Power=0
Write IC File=0
Echo Input=False
Echo Output=False
Write Detailed=0

--- RublesRun.f01 (steady flow) ---

Flow Title=NFF Regression Equation
Program Version=4.10
Number of Profiles= 1
Profile Names=P100yr
River Rch & RM=RublesRun,Main            ,14499.7
    1788
River Rch & RM=RublesRun,Main            ,8221.6
    1938
River Rch & RM=RublesRun,Main            ,5252.1
    2057
River Rch & RM=RublesRun,Main            ,907.8
    2115
Boundary for River Rch & Prof#=RublesRun,Main            , 1
Up Type= 0
Dn Type= 1
Dn Known WS=880
DSS Import GetInterval= 0
DSS Import GetPeak= 0
DSS Import FillOption= 0

--- RublesRun.g01 (geometry) ---

Geom Title=USGS 10m DEM
Program Version=4.10

River Reach=RublesRun       ,Main
Reach XY= 30
     1879907.081      445225.784     1879568.743      444514.446
     1879261.826      444086.847     1878953.626      443999.439
     1878622.934      443736.633     1878137.879       443616.71
     1877725.548      443833.714     1877454.584      444366.319
     1877109.673      444555.119     1876926.578      444835.177
     1876874.547      445123.951     1876721.054      445233.217
     1876349.029      445274.842     1876237.162      445225.412
     1875982.208      445079.724     1875555.609      444653.636
     1874855.727       445238.42     1874583.513      445270.915
     1874097.774      445577.902     1873395.182      445009.343
     1873090.079      444331.762     1872450.323      443642.794
     1872450.323      443445.946     1872745.595      442855.402
     1872351.899      442166.434     1872302.687      441674.314
     1872007.415      441477.466     1871460.568      441533.371
     1871008.305      441370.596     1870727.903      441379.042

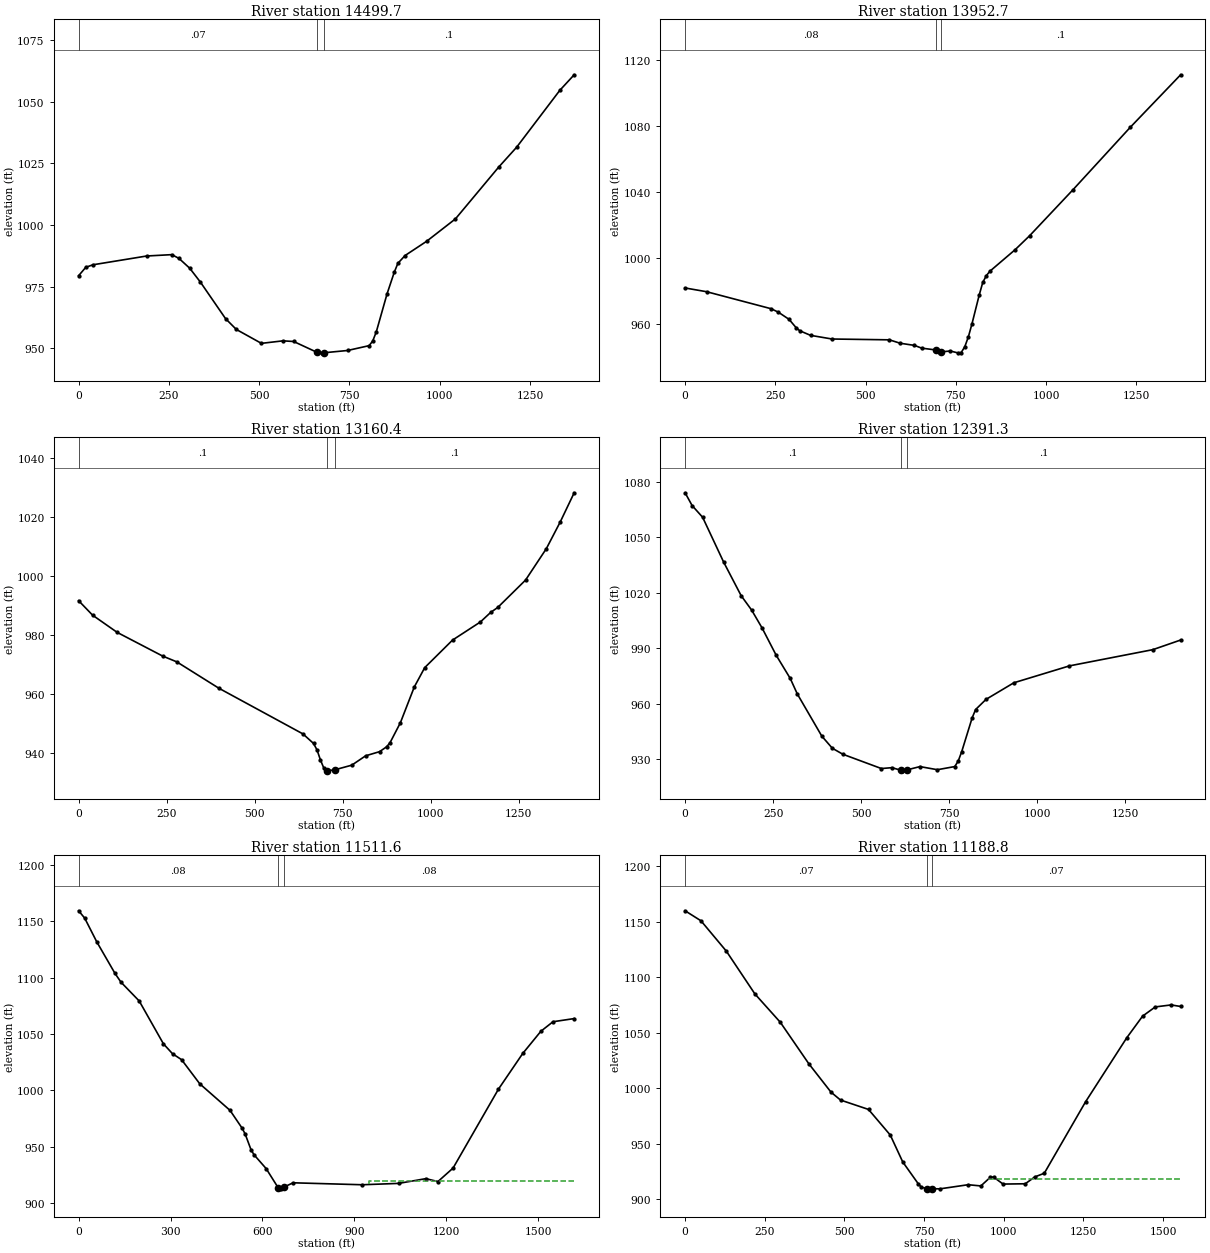
Type RM Length L Ch R = 1 ,14499.7 ,547.6,547,546.8
XS GIS Cut Line= 3
      1880468.17      444812.215      1879889.69      445179.067
     1879329.515      445577.904
#Sta/Elev= 30
       0  979.49    19.8  982.89    39.7  983.91   188.6  987.47   258.1  988.02
     278  986.49   307.8   982.5   337.5  976.85     407  962.08   436.8  957.71
   506.3  952.07   565.9  953.09   595.6  952.83   658.9  948.53   673.9  948.23
  678.66 948.248   744.8  949.18   804.6  951.14   814.6  953.02   824.5  956.73
   854.4  972.18   874.4  980.94   884.3   984.5   904.2  987.66     964  993.44
  1043.8 1002.52  1163.4 1023.47  1213.2 1031.54  1332.8 1054.59  1372.6  1060.9
#Mann= 3 , 0 , 0
       0     .07       0   658.9    .045       0  678.66      .1       0
Bank Sta=658.9,678.66
XS Rating Curve= 0 ,0
Exp/Cntr=0.3,0.1

Type RM Length L Ch R = 1 ,13952.7 ,806.6,792.3,778.3
XS GIS Cut Line= 3
     1880232.059      444319.159     1879653.579      444686.012
     1879093.404      445084.848
#Sta/Elev= 30
       0   981.6    59.6  979.33   238.3  969.01   258.1  966.93   287.9  962.58
   307.8  957.44   317.7  955.64   347.5  952.86     407  950.64   565.9  950.14
   595.6  948.08   635.4  946.76   655.2  945.11   694.5  943.99   709.5  942.86
   734.8  943.36   754.8  942.25   764.7  942.42   774.7  945.95   784.7  951.99
   794.6  959.83   814.6  977.26   824.5  984.96   834.5  989.12   844.4  991.79
   914.2 1004.83   954.1 1013.25  1073.7 1041.03  1233.1 1079.08  1372.6 1110.94
#Mann= 3 , 0 , 0
       0     .08       0   694.5    .045       0   709.5      .1       0
Bank Sta=694.5,709.5
XS Rating Curve= 0 ,0
Exp/Cntr=0.3,0.1

Type RM Length L Ch R = 1 ,13160.4 ,767.4,769.2,768.2
XS GIS Cut Line= 3
     1879495.709      443392.098     1879221.459      444011.225
     1878977.511      444699.705
#Sta/Elev= 30
       0  991.68    39.8  986.76   109.5  980.94     239  972.89   278.8  970.95
   398.3  962.01   637.3  946.51   667.2  943.29   677.2  941.09     687  937.64
   696.9  934.82  706.25934.0455   706.8     934   728.5  934.38   775.8  935.92
   815.3   939.1   854.8   940.5   874.6  942.13   884.4   943.5     914  950.32
   953.5  962.45   983.1  968.99  1062.1  978.33  1141.1  984.46  1170.7  987.74
  1190.4  989.38  1269.4  998.66  1328.6 1009.34  1368.1  1018.4  1407.6 1028.27
#Mann= 3 , 0 , 0
       0      .1       0  706.25    .045       0   728.5      .1       0
Bank Sta=706.25,728.5
XS Rating Curve= 0 ,0
Exp/Cntr=0.3,0.1

Type RM Length L Ch R = 1 ,12391.3 ,893.6,879.7,867
XS GIS Cut Line= 3
     1878772.607      443152.525     1878532.113      443785.529
     1878325.613      444486.153
#Sta/Elev= 30
       0 1074.02    19.9 1067.12    49.8 1060.77   109.5 1036.53   159.3 1018.35
   189.2 1010.53   219.1 1000.76   258.9   986.1   298.7  973.61   318.7  965.24
   388.4   942.4   418.2  935.87   448.1  932.62   557.6  924.89   587.5  925.37
   614.2  923.91   617.4  923.65   629.2  924.13   667.2  925.94   716.6  924.26
     766  925.96   775.8  928.94   785.7     934   815.3  952.26   825.2   956.8
   854.8   962.3   933.8  971.27  1091.7  980.41  1328.6  989.18  1407.6  994.39
#Mann= 3 , 0 , 0
       0      .1       0   614.2    .045       0   629.2      .1       0
Bank Sta=614.2,629.2
XS Rating Curve= 0 ,0
Exp/Cntr=0.3,0.1

Type RM Length L Ch R = 1 ,11511.6 ,307.4,322.8,330.5
XS GIS Cut Line= 4
      1877721.37      443162.314     1877747.412      443685.751
     1877796.963      444014.864     1878052.171      444731.877
#Sta/Elev= 30
       0 1159.21    19.8 1152.69    59.3 1131.62   118.7 1103.68   138.4 1095.86
   197.8 1079.23   276.9 1041.23   306.5 1032.47   336.2 1027.17   395.5  1005.8
   494.4  982.22   533.9  966.38   543.7   961.3   563.2  947.08     573  942.77
   612.2  930.63   651.3  913.71   661.1  912.65   670.9  914.28   700.3  918.01
   926.1  916.27  1044.7  917.48  1133.7  921.68  1173.2   919.1  1222.6  931.07
  1370.9  1001.1    1450 1032.66  1509.3 1052.37  1548.8 1060.82    1618 1063.62
#Mann= 3 , 0 , 0
       0     .08       0   651.3    .045       0   670.9     .08       0
#XS Ineff= 2 , 0
                          948.97          919.26
Permanent Ineff=
       F       F
Bank Sta=651.3,670.9
XS Rating Curve= 0 ,0
Exp/Cntr=0.3,0.1

Type RM Length L Ch R = 1 ,11188.8 ,359.3,335.8,319.7
XS GIS Cut Line= 4
     1877468.766      443318.564     1877531.266      443792.522
     1877609.391      444164.918      1877783.87      444839.397
#Sta/Elev= 30
       0 1159.66    49.8 1150.65   129.5  1123.3   219.1 1084.79   298.8 1059.29
   388.4  1021.9   458.1  996.32   487.8  989.27   575.6  980.82   643.9  957.77
     683  933.58   731.7  913.92   741.5  910.81   759.4  909.47   774.4  909.43
     800  909.34   888.4  913.05   928.2  911.95   958.1   919.8     968  919.96
   997.9  913.63  1067.6   913.9  1097.4  920.06  1127.3  923.38  1256.7  987.64
    1386 1045.28  1435.8 1064.81  1475.6 1073.11  1525.4  1074.9  1555.2 1073.52
#Mann= 3 , 0 , 0
       0     .07       0   759.4    .045       0   774.4     .07       0
#XS Ineff= 2 , 0
                          950.44          918.25
Permanent Ineff=
       F       F
Bank Sta=759.4,774.4
XS Rating Curve= 0 ,0
Exp/Cntr=0.3,0.1

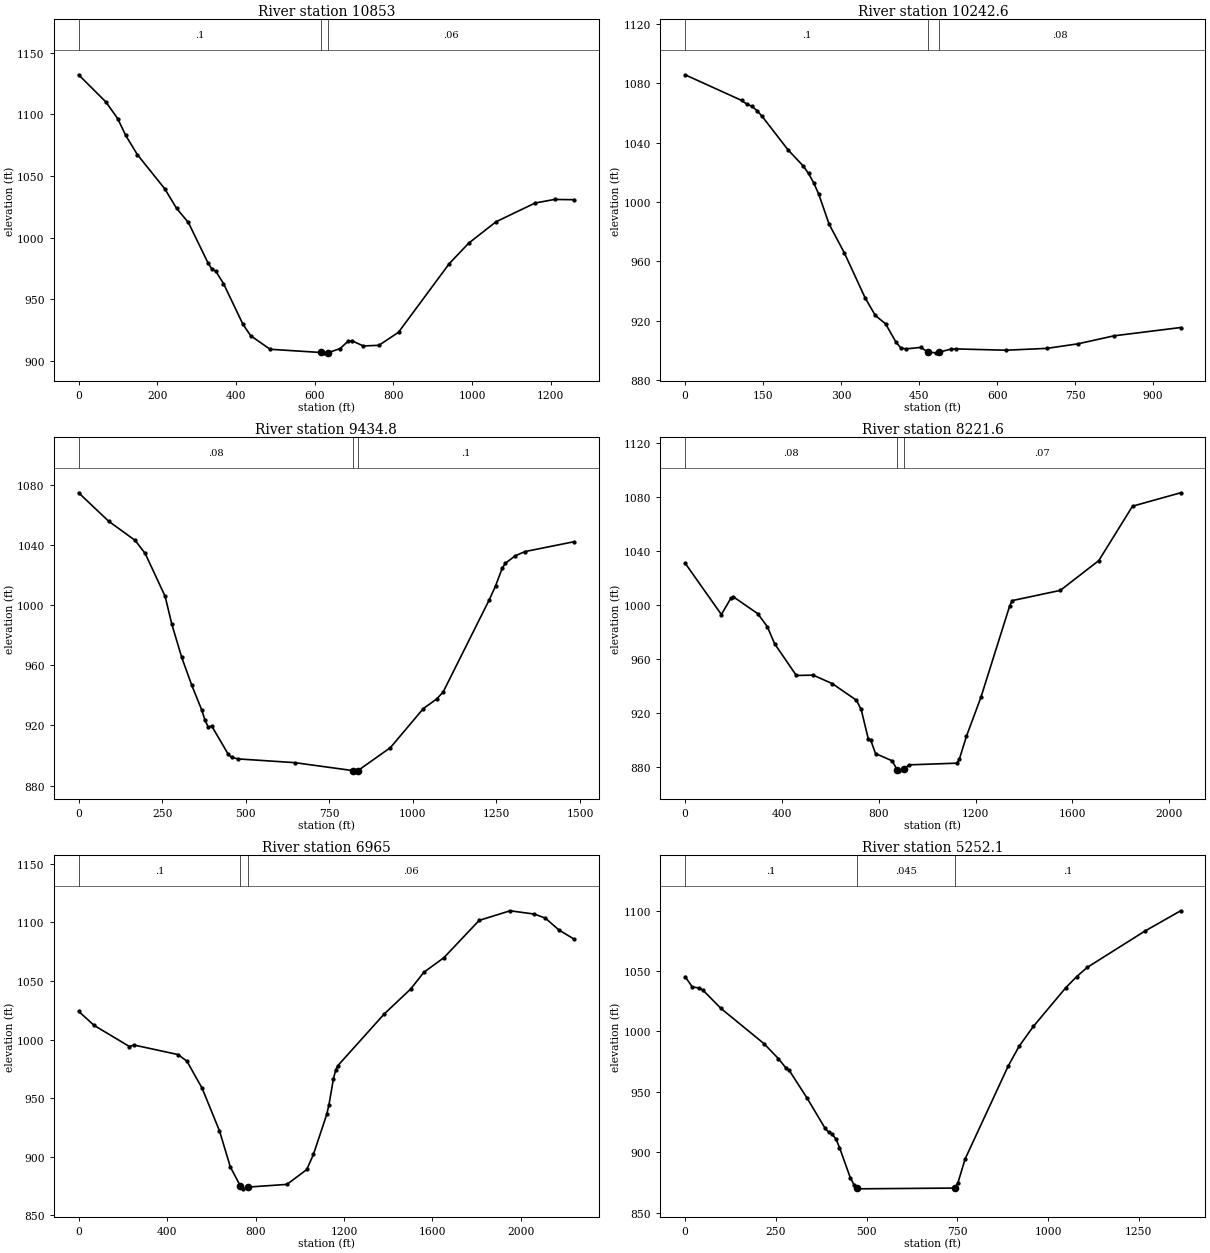
Type RM Length L Ch R = 1 ,10853   ,617.2,610.4,603.7
XS GIS Cut Line= 4
     1877128.488      443835.925     1877298.627      444117.175
     1877493.071      444460.925     1877726.053      444943.503
#Sta/Elev= 30
       0 1132.17    69.7 1109.99    99.6 1096.46   119.5 1083.07   149.4 1067.36
   219.1 1039.62     249 1023.84   278.9 1012.37   328.7  979.66   338.6  974.52
   348.4  972.92   368.2  962.86   417.6  929.84   437.3  920.54   486.7  909.55
     615  906.96   624.9  906.66   634.7  906.86   664.4  910.08   684.2  915.89
     694  916.51   723.6  912.24   763.3  912.77     813  923.33     942     979
   991.6  995.66    1061 1012.97  1160.3 1028.18  1209.9 1031.07  1259.5 1030.85
#Mann= 3 , 0 , 0
       0      .1       0     615    .045       0   634.7     .06       0
Bank Sta=615,634.7
XS Rating Curve= 0 ,0
Exp/Cntr=0.3,0.1

Type RM Length L Ch R = 1 ,10242.6 ,790,807.7,825.1
XS GIS Cut Line= 4
     1876667.659      444376.264     1876941.096      444688.764
     1877058.779      444814.445     1877308.575      445081.219
#Sta/Elev= 30
       0 1085.64   108.8 1068.37   118.6 1065.89   128.5  1064.4   138.4  1061.5
   148.3 1057.58   197.7 1035.21   227.4 1024.17   237.3 1019.21   247.2    1013
     257 1005.26   276.8  985.18   306.5  965.58     346  935.63   365.8  923.64
   385.6  917.98   405.4  905.73   415.2  901.66   424.8  901.17   453.5  902.14
  466.42899.0739   482.2  898.49  487.65898.8744   510.9  900.97   520.5  901.13
     617  900.26   696.1  901.51   755.3  904.55   824.5  909.93   952.9  915.53
#Mann= 3 , 0 , 0
       0      .1       0  466.42    .045       0  487.65     .08       0
Bank Sta=466.42,487.65
XS Rating Curve= 0 ,0
Exp/Cntr=0.3,0.1

Type RM Length L Ch R = 1 ,9434.8  ,1211.2,1213.2,1215.1
XS GIS Cut Line= 4
      1876528.77      444406.646      1876528.77      444983.903
     1876515.749      445487.375     1876559.152      445886.681
#Sta/Elev= 30
       0 1074.58    89.6 1055.73   169.2 1042.92   199.1 1034.24   258.8 1005.76
   278.7  987.34   308.5  965.15   338.4  946.76   368.2  930.32   378.2  923.38
   388.2  918.86   398.1  919.64   447.9  900.74   457.8  898.75   477.7  897.76
   646.4  895.29   820.1  890.01     834  889.84   835.1  889.91   932.8  905.27
  1031.5  931.24    1071  937.52  1090.7  942.26  1227.8 1003.14  1247.4 1012.69
    1267 1024.31  1276.8 1027.77  1306.2 1032.71  1335.6 1035.53  1482.6 1042.08
#Mann= 3 , 0 , 0
       0     .08       0   820.1    .045       0   835.1      .1       0
Bank Sta=820.1,835.1
XS Rating Curve= 0 ,0
Exp/Cntr=0.3,0.1

Type RM Length L Ch R = 1 ,8221.6  ,1263.6,1256.6,1249.8
XS GIS Cut Line= 4
     1875790.923      443807.688      1875586.93      444328.521
     1875521.826      444858.035     1875604.291      445808.556
#Sta/Elev= 30
       0    1031   149.8  992.95   189.8 1005.21   199.8 1005.99   299.7  993.64
   339.6  984.01   369.6  971.38   459.5  947.85   529.4  948.08   608.8  941.73
   707.6  929.53   727.3   922.7     757  900.73   766.8  899.96   786.6  890.06
   855.8  884.64   875.5   878.1   885.4  877.26   905.2  878.71   924.9  881.68
  1122.7  882.94  1132.6  885.76  1162.4  902.95  1222.1  931.74  1341.3  999.59
  1351.3 1003.25    1550 1010.82    1709 1032.88  1848.2 1073.12    2047 1083.05
#Mann= 3 , 0 , 0
       0     .08       0   875.5    .045       0   905.2     .07       0
Bank Sta=875.5,905.2
XS Rating Curve= 0 ,0
Exp/Cntr=0.3,0.1

Type RM Length L Ch R = 1 ,6965    ,1679.6,1712.9,1744.1
XS GIS Cut Line= 4
      1874430.68      444571.142     1874484.499      445057.688
     1874571.305      445491.715     1874770.958      446785.118
#Sta/Elev= 30
       0 1024.06    69.9 1012.09   229.8  994.01   249.8  995.33   449.6  987.15
   489.5  981.55   558.4  958.45     637  922.01   686.2  891.09   730.4  875.37
   745.2  872.52   764.9     874   942.1  876.32    1032  889.04    1062  902.05
    1122   936.1  1131.9  944.21  1151.9  966.04  1161.9  973.68  1171.9  977.64
  1381.7 1021.77  1501.6 1043.13  1561.5 1057.48  1651.4  1069.8  1811.3 1101.71
  1951.1 1109.92    2061  1107.1    2111 1103.62  2170.9 1093.66  2240.9 1085.66
#Mann= 3 , 0 , 0
       0      .1       0   730.4    .045       0   764.9     .06       0
Bank Sta=730.4,764.9
XS Rating Curve= 0 ,0
Exp/Cntr=0.3,0.1

Type RM Length L Ch R = 1 ,5252.1  ,1378.1,1384.4,1390.6
XS GIS Cut Line= 3
     1873832.363      444478.027     1873219.168      444777.691
     1872605.973      445077.355
#Sta/Elev= 30
       0 1045.32    19.8 1036.79    39.6 1035.85    49.5    1034    98.9 1018.95
   217.6  989.77   257.2  977.39     277  970.02   286.8  967.73   336.3  944.63
   385.8   919.7   395.6  916.58   405.5  914.74   415.4     911   425.3   903.9
     455  878.94   464.9  873.27   473.1 870.313   474.8   869.7  743.03870.3461
   751.7   874.9   771.5  894.54   890.2  971.41   919.9  987.66   959.5 1004.16
  1048.5 1036.08  1078.2  1045.2  1107.8 1052.95  1266.1  1082.9    1365 1099.79
#Mann= 3 , 0 , 0
       0      .1       0   473.1    .045       0  743.03      .1       0
Bank Sta=473.1,743.03
XS Rating Curve= 0 ,0
Exp/Cntr=0.3,0.1

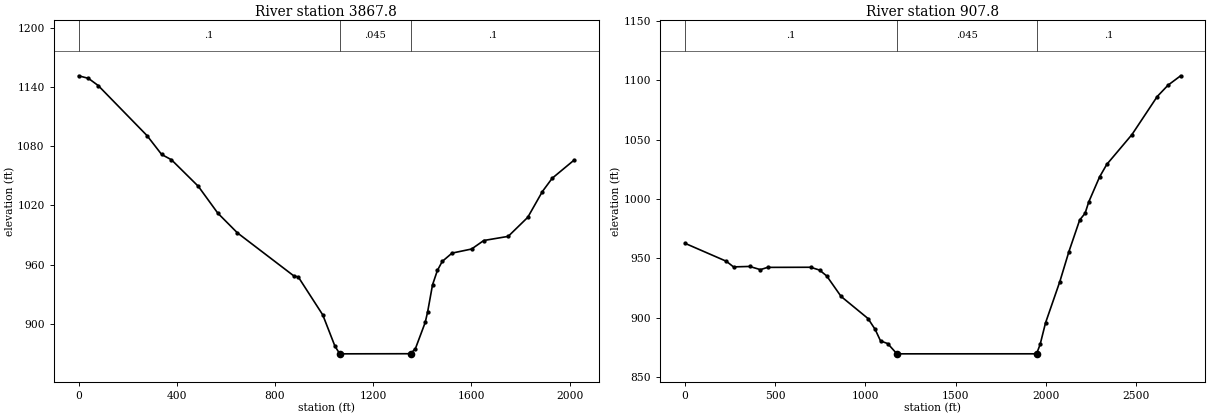
Type RM Length L Ch R = 1 ,3867.8  ,2977.1,2959.9,2942.2
XS GIS Cut Line= 4
     1873667.659      443420.101     1872958.349      443575.508
     1872177.099      443721.341     1871687.516      443809.883
#Sta/Elev= 30
       0  1151.3    39.8 1148.69    79.6 1141.44   278.5 1090.74   338.2 1071.59
     378 1066.26   487.4 1039.38     567 1012.14   646.6  992.24   875.2  948.88
     895  947.43   994.4  909.13    1044  877.45 1063.35869.8478  1063.9   869.7
    1352  869.82  1371.9  875.09  1411.6  901.47  1421.5  912.15  1441.4  939.53
  1461.3  954.19  1481.1   963.3  1520.9  971.71  1600.5  975.85  1650.2  984.48
  1749.7  988.66  1829.4 1007.97    1889 1034.09  1928.8  1047.5  2018.4 1065.98
#Mann= 3 , 0 , 0
       0      .1       0 1063.35    .045       0    1352      .1       0
Bank Sta=1063.35,1352
XS Rating Curve= 0 ,0
Exp/Cntr=0.3,0.1

Type RM Length L Ch R = 1 ,907.8   ,932.4,907.8,883.6
XS GIS Cut Line= 4
     1872999.256       441058.99     1872027.034      440850.656
     1871454.117      441770.795      1871497.52      442439.198
#Sta/Elev= 30
       0  962.67   228.7  947.59   268.5  942.85     358  943.24   417.6  940.55
   457.4  942.45     696  942.55   745.7  940.18   785.5   935.2     865     918
  1014.2  899.43    1054  890.25  1083.8  880.58  1123.6  878.32  1173.3  869.93
  1183.2   869.7 1948.99869.7251  1968.8  877.58  1998.7  895.72  2078.2  930.55
  2128.2  955.62  2188.2  982.32  2218.2  987.99  2238.2  997.44  2298.2 1018.47
  2338.1 1029.04  2478.1 1054.21  2618.1  1086.2    2678 1095.75    2748 1103.67
#Mann= 3 , 0 , 0
       0      .1       0  1173.3    .045       0 1948.99      .1       0
Bank Sta=1173.3,1948.99
XS Rating Curve= 0 ,0
Exp/Cntr=0.3,0.1

Chan Stop Cuts=-1
Use User Specified Reach Order=0
Composite Channel Slope=5